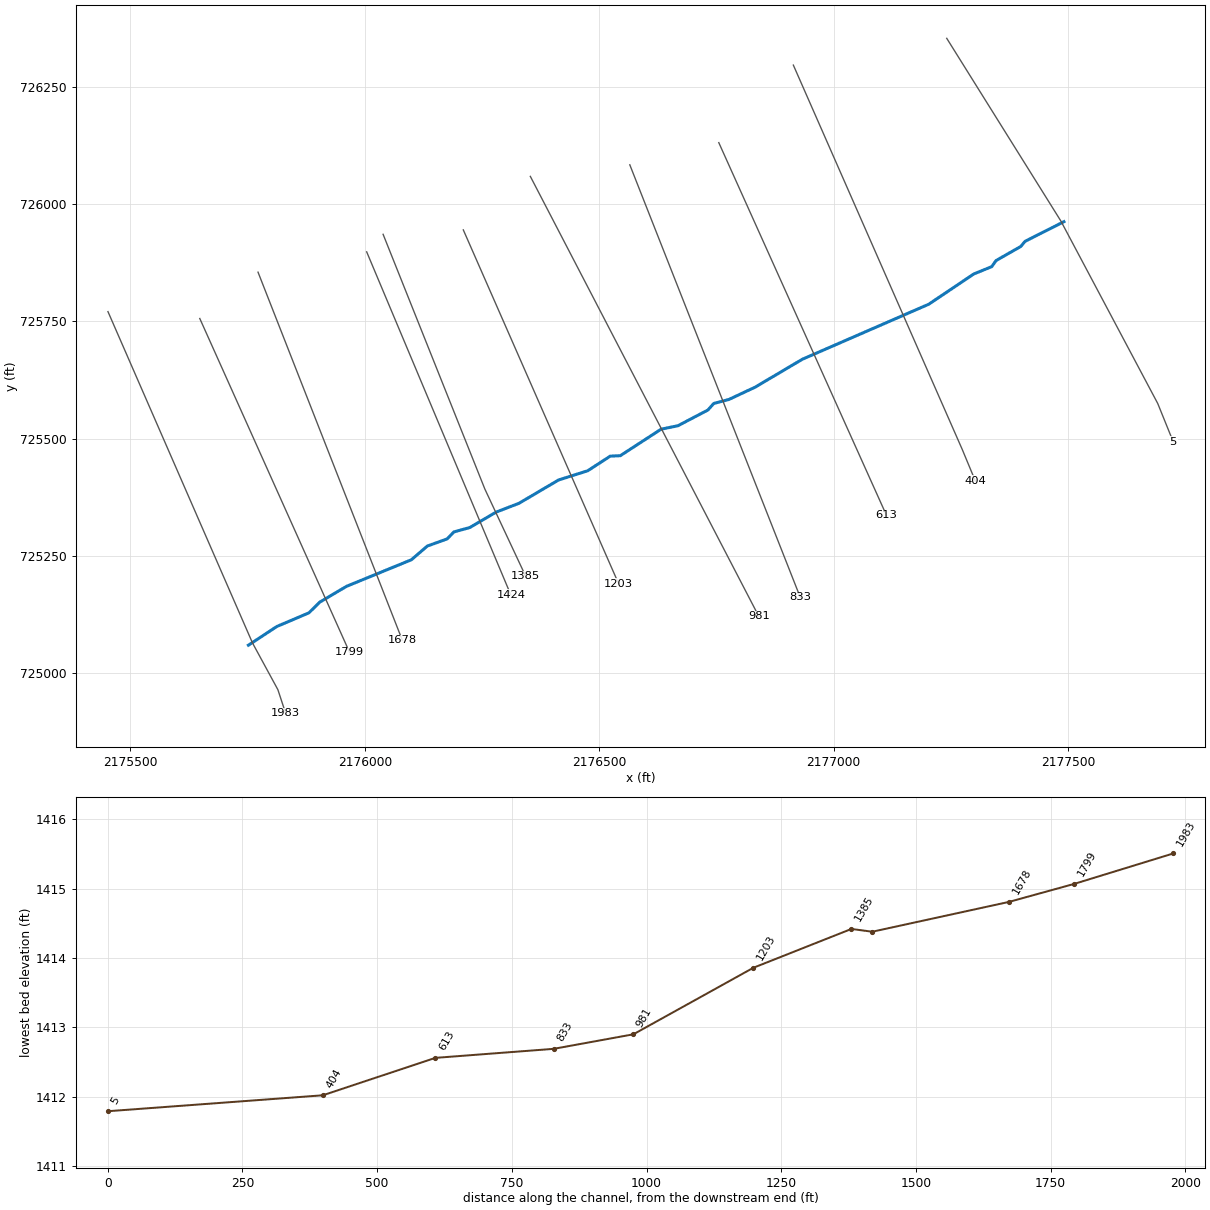
--- BRUSHYFK.prj (project) ---

Proj Title=BRUSHYFK
Current Plan=p01
Default Exp/Contr=0,0
English Units
Geom File=g01
Flow File=f01
Plan File=p01
BEGIN DESCRIPTION:
---------- MODELED AS PART OF WVEMD CTP PROGRAM, 2023----------
Stream Name: Brushy Fork
Flood Zone:  AFH
Upshur County, WV
HEC-RAS Version: RAS 6.3
Vertical Datum: NAVD88
Projection: NAD 1983 StatePlane West Virginia S FIPS 4702 (US Feet)
Terrain: 1-meter LIDAR (FEMA Region III 3DEP collected 2016-2018)
Land Use: 2019 NLCD
Hydrologic Method:
WV SIR2010-5033 regression equations
Additional Model Notes:
None
END DESCRIPTION:
DSS Export Rating Curves= 0
DSS Export Rating Curve Sorted= 0
DSS Export Volume Flow Curves= 0
DXF OffsetX= 0
DXF OffsetY= 0
DXF ScaleX= 0
DXF ScaleY= 0

--- BRUSHYFK.p01 (plan) ---

Plan Title=Floodplain
Program Version=6.30
Short Identifier=Floodplain
Geom File=g01
Flow File=f01
Subcritical Flow
K Sum by GR= 0
Std Step Tol= 0.01
Critical Tol= 0.01
Num of Std Step Trials= 20
Max Error Tol= 0.3
Flow Tol Ratio= 0.001
Split Flow NTrial= 30
Split Flow Tol= 0.02
Split Flow Ratio= 0.02
Log Output Level= 0
Friction Slope Method= 1
Unsteady Friction Slope Method= 2
Unsteady Bridges Friction Slope Method= 1
Parabolic Critical Depth
Global Vel Dist= 0 , 0 , 0
Global Log Level= 0
CheckData=False
Encroach Param=-1 ,0,0, 0
Mapping Interval=1HOUR
Computation Time Step Use Courant=        0
Computation Time Step Use Time Series=    0
Computation Time Step Count To Double=0
Computation Time Step Max Doubling=0
Computation Time Step Max Halving=0
Computation Time Step Residence Courant=0
Run HTab= 0
Run UNet= 0
Run Sediment= 0
Run PostProcess= 0
Run WQNet= 0
Run RASMapper=-1
UNET Theta= 0
UNET Theta Warmup= 0
UNET ZTol= 0
UNET ZSATol= 0
UNET MxIter= 0
UNET Max Iter WO Improvement= 0
UNET MaxInSteps= 0
UNET DtIC= 0
UNET DtMin= 0
UNET MaxCRTS= 0
UNET WFStab= 0
UNET SFStab= 0
UNET WFX= 1
UNET SFX= 1
UNET Gravity=32.17405
UNET 1D Methodology=Finite Difference
UNET DSS MLevel= 1
UNET Pardiso=0
UNET DZMax Abort= 0
UNET Use Existing IB Tables= 0
UNET Froude Reduction=False
UNET Froude Limit= 0
UNET Froude Power= 0
UNET D1 Cores= 0
UNET WindReference=Eulerian
UNET WindDragFormulation=Hsu (1988)
UNET D2 Coriolis=0
UNET D2 Cores= 0
UNET D2 Theta= 1
UNET D2 Theta Warmup= 1
UNET D2 Z Tol= 0.01
UNET D2 Volume Tol= 0.01
UNET D2 Max Iterations= 20
UNET D2 Equation= 0
UNET D2 RampUpFraction=0.1
UNET D2 TimeSlices= 1
UNET D2 Turbulence Formulation=Non-Conservative (original)
UNET D2 Eddy Viscosity=0.3
UNET D2 Transverse Eddy Viscosity=0.1
UNET D2 Smagorinsky Mixing=0
UNET D2 BCVolumeCheck=0
UNET D2 Cores=0
UNET D2 SolverType=PARDISO (Direct)
UNET D2 Minimum Iterations= 3
UNET D2 Maximum Iterations= 30
UNET D2 Restart Number= 10
UNET D2 Relaxation Coeff=1.3
UNET D2 SOR Precondition Iterations= 10
UNET D2 ILUT Maximum Fill= 8
UNET D2 ILUT Tolerance=1E-08
UNET D2 Convergence Tolerance=0.00001
UNET D1D2 MaxIter= 0
UNET D1D2 ZTol=0.01
UNET D1D2 QTol=0.1
UNET D1D2 MinQTol=1
Write IC File= 0
Write IC File at Fixed DateTime=0
Write IC File at Sim End=0
Echo Input=False
Echo Parameters=False
Echo Output=False
Write Detailed= 0
HDF Write Warmup=0
HDF Write Time Slices=0
HDF Flush=0
HDF Compression= 1
HDF Chunk Size= 1
HDF Spatial Parts= 1
HDF Use Max Rows=0
HDF Fixed Rows= 1
Calibration Method= 0
Calibration Iterations= 20
Calibration Max Change=0.05
Calibration Tolerance=0.2
Calibration Maximum=1.5
Calibration Minimum=0.5
Calibration Optimization Method= 1
WQ AD Non Conservative
WQ ULTIMATE=-1
WQ Max Comp Step=1HOUR
WQ Output Interval=15MIN
WQ Output Selected Increments= 0
WQ Output face flow=0
WQ Output face velocity=0
WQ Output face area=0
WQ Output face dispersion=0
WQ Output cell volume=0
WQ Output cell surface area=0
WQ Output cell continuity=0
WQ Output cumulative cell continuity=0
WQ Output face conc=0
WQ Output face dconc_dx=0
WQ Output face courant=0
WQ Output face peclet=0
WQ Output face adv mass=0
WQ Output face disp mass=0
WQ Output cell mass=0
WQ Output cell source sink temp=0
WQ Output nsm pathways=0
WQ Output nsm derived pathways=0
WQ Create Restart=0
WQ Fixed Restart=0
WQ System Summary=0
WQ Write To DSS=0
Sorting and Armoring Iterations= 10
XS Update Threshold= 0.02
Bed Roughness Predictor= 0
Hydraulics Update Threshold= 0.02
Energy Slope Method= 1
Volume Change Method= 1
Sediment Retention Method= 0
Sediment TS Multiplier= 1
Warm Up Method= 0
XS Weighting Method= 0
Number of US Weighted Cross Sections= 1
Number of DS Weighted Cross Sections= 1
Upstream XS Weight=0
Main XS Weight=1
Downstream XS Weight=0
Number of DS XS's Weighted with US Boundary= 1
Upstream Boundary Weight= 1
Weight of XSs Associated with US Boundary= 0
Number of US XS's Weighted with DS Boundary= 1
Downstream Boundary Weight= 0.5
Weight of XSs Associated with DS Boundary= 0.5
Percentile Method= 0
Sediment Output Level= 3
Mass or Volume Output= 0
Output Increment Type= 1
Profile and TS Output Increment= 1
Transport Output Increment 1
XS Output Flag= 0
XS Output Increment= 10
Read HDF5 Sediment Hotstart= 0
Sediment Hotstart Type= 0
Write Gradation File= 0
Read Gradation Hotstart= 0
Write HDF5 File= 1
Write Binary Output= 1
Write DSS Sediment File= 0
DSS Sediment Output Type= 1
SV Curve= 0
Specific Gage Flag= 0
Subcell Erosion Methods= 0
Subcell Deposition Methods= 0
Advection Scheme= 1
Matrix Solver= 0
Implicit Weighting Factor= 1
Maximum Outer Loop Convergence Iterations= 5
Convergence Maximum Absolute= 0.001
Convergence RMSE= 0.0001
Grain Fractions Max Abs Error= 0.001
Max Subgrid Regions= 1
Max Subgrid Length Scale= 3.402823E+38
Initial Layer Thickness= 3.402823E+38
Min Layer Thickness= 3.402823E+38
Max Layer Thickness= 3.402823E+38
Number of Layers= 5

--- BRUSHYFK.f01 (steady flow) ---

Flow Title=Flows
Program Version=4.00
Number of Profiles= 1
Profile Names=01pct
River Rch & RM=BRUSHYFK,Main,1983
     434
River Rch & RM=BRUSHYFK,Main,1424
     499
Boundary for River Rch & Prof#=BRUSHYFK,Main      ,1
Up Type=0
Dn Type=3
Dn Slope=0.000538

--- BRUSHYFK.g01 (geometry) ---

Geom Title=Geometry
Program Version=6.31

River Reach=BRUSHYFK        ,Main
Reach XY= 30
     2175751.697      725059.223     2175812.278      725099.086
     2175880.728      725128.189     2175903.907      725151.082
     2175961.169      725184.878       2176099.5       725241.51
     2176133.268       725270.67      2176175.82      725286.037
     2176189.871      725300.746     2176223.953      725310.246
     2176280.356      725343.212     2176328.946      725361.927
     2176413.336      725411.663      2176475.52      725431.322
     2176523.595      725462.543     2176545.057      725463.487
     2176632.108      725520.033     2176668.022      725527.359
     2176731.837      725560.869     2176744.342      725574.833
     2176776.678      725583.418     2176832.452      725609.516
      2176933.41       725669.21      2177203.12      725786.623
     2177299.185      725851.182     2177337.388       725866.72
      2177346.66       725879.77     2177399.428      725909.817
       2177408.5      725920.748     2177491.401      725962.671

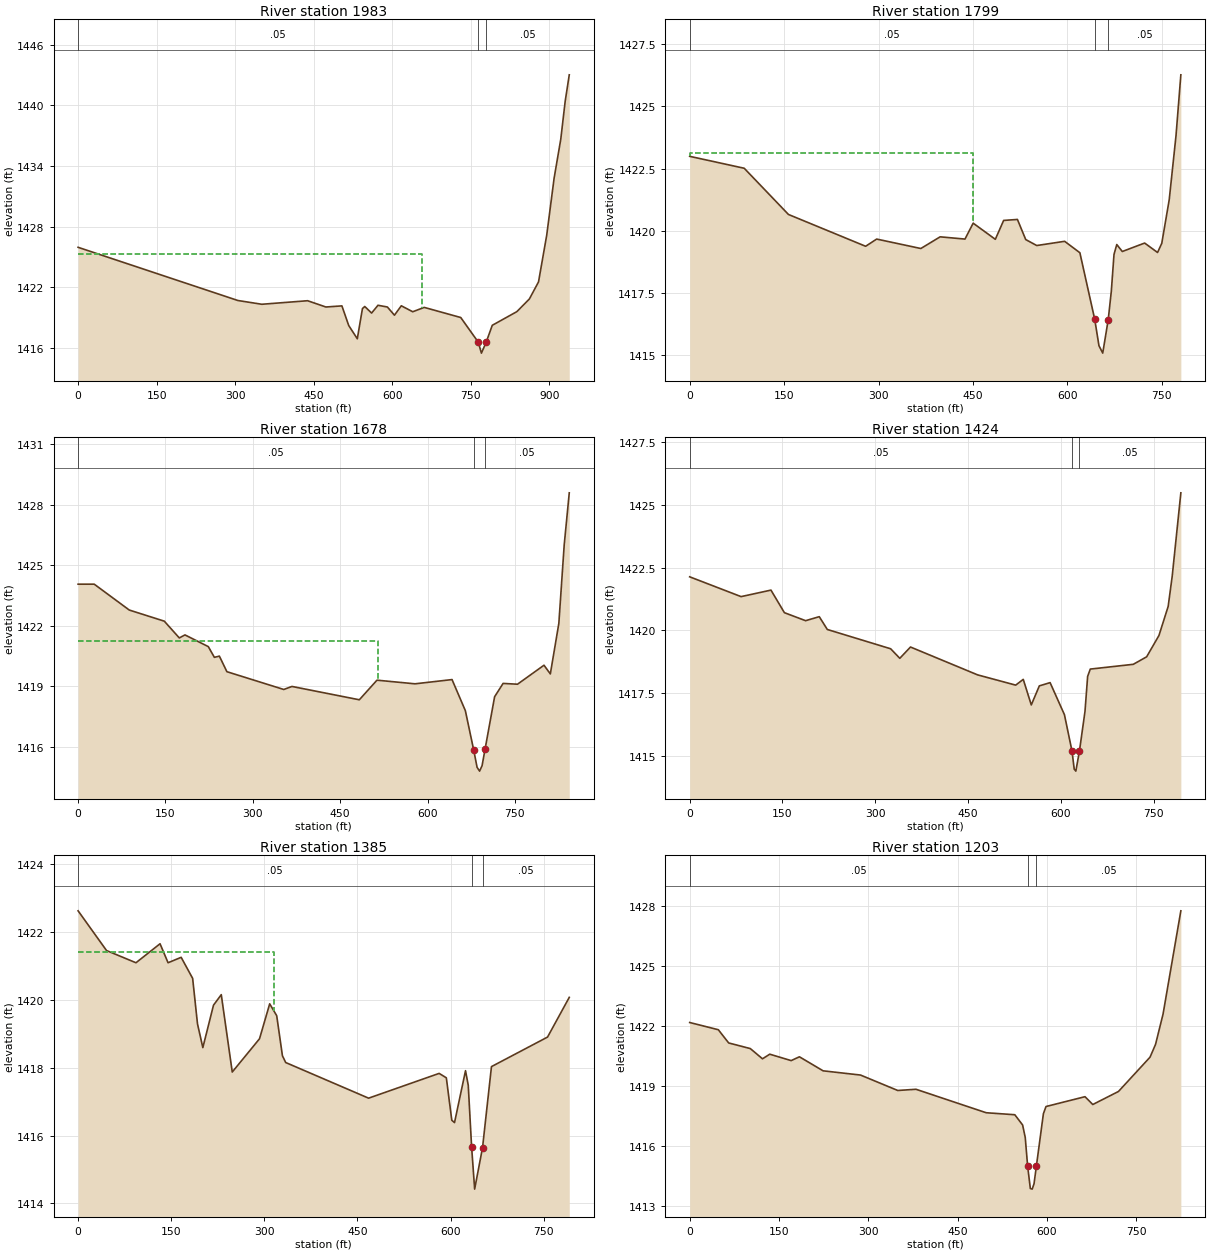
Type RM Length L Ch R = 1 ,1983    ,180.7,184.2,180.7
XS GIS Cut Line= 4
2175452.06625124725770.822629493     2175760.413      725063.949
2175814.58212616724964.2642586042175831.15871536724913.762839001
#Sta/Elev= 30
       0 1425.97   305.2 1420.71   350.8 1420.34   438.2 1420.69   473.1 1420.07
   503.7 1420.18   516.7 1418.24   533.1 1416.93   542.9 1419.91   547.3 1420.12
   560.4 1419.47   572.6 1420.24   590.5 1420.07     604 1419.26   617.1 1420.19
   638.9  1419.6   660.9 1420.03   730.6 1419.03     764  1416.6   770.1 1415.51
   779.1 1416.58   790.8 1418.26   837.7 1419.61   861.6 1420.86   879.1 1422.55
   894.7 1427.15   908.9 1432.81   921.6 1436.66     930  1440.4   937.8 1443.02
#Mann= 3 ,-1,0
       0     .05       0     764    .045       0   779.1     .05       0
#XS Ineff= 2 , 0
           656.9 1425.35
Permanent Ineff=
       F       F
Bank Sta=764,779.1
XS Rating Curve= 0 ,0
Exp/Cntr=0.3,0.1

Type RM Length L Ch R = 1 ,1799    ,121.7,121.2,120.3
XS GIS Cut Line= 2
 2175647.9423137725756.1574179622175967.32179954725044.348883026
#Sta/Elev= 30
       0 1422.99    86.6 1422.51   156.9 1420.65   279.5 1419.37     297 1419.66
   367.2 1419.28   397.8 1419.75   437.3 1419.66   450.3  1420.3   485.5 1419.65
   498.7 1420.41   520.6 1420.45   533.8 1419.64   551.3  1419.4   595.6 1419.57
   619.8 1419.11   643.4 1416.43   650.1 1415.37   656.1 1415.07   664.81416.411
   669.7 1417.55     674 1419.04   678.4 1419.44   687.2 1419.16   722.7  1419.5
   743.2 1419.12   749.9 1419.49   761.7 1421.24   772.5 1423.82   780.2 1426.27
#Mann= 3 ,-1,0
       0     .05       0   643.4    .045       0   664.8     .05       0
#XS Ineff= 2 , 0
          450.25 1423.11
Permanent Ineff=
       F       F
Bank Sta=643.4,664.8
XS Rating Curve= 0 ,0
Exp/Cntr(USF)=0,0
Exp/Cntr=0.3,0.1

Type RM Length L Ch R = 1 ,1678    ,251.4,253.5,252.2
XS GIS Cut Line= 2
2175772.18724763725855.0053628032176080.03159496725069.783728892
#Sta/Elev= 30
       0 1424.06    27.7 1424.06    87.9 1422.78     148 1422.23   173.8  1421.4
   183.5 1421.55   223.6 1420.97     234 1420.44   242.6  1420.5   255.5 1419.73
   353.2 1418.85   367.2    1419   482.9 1418.34   513.2 1419.31   578.6 1419.13
   642.1 1419.34     665  1417.8   679.4 1415.84   685.1    1415   689.4 1414.81
   693.7 1415.08   698.9 1415.91   715.2 1418.49   729.8 1419.15   754.5 1419.11
     800 1420.05   810.9 1419.62   825.5 1422.12   834.7    1426   843.4 1428.58
#Mann= 3 ,-1,0
       0     .05       0   679.4    .045       0   698.9     .05       0
#XS Ineff= 2 , 0
          514.93 1421.25
Permanent Ineff=
       F       F
Bank Sta=679.4,698.9
XS Rating Curve= 0 ,0
Exp/Cntr=0.3,0.1

Type RM Length L Ch R = 1 ,1424    ,38.5,38.8,39.3
XS GIS Cut Line= 2
2176003.97478433725898.3270104082176311.61191305725166.271790942
#Sta/Elev= 30
       0 1422.13    83.1 1421.34   131.4  1421.6   153.1  1420.7   187.4 1420.38
   209.5 1420.54   222.5 1420.03   324.9 1419.26   339.7 1418.88     357 1419.33
   465.4 1418.22   527.1 1417.81   539.3 1418.04   552.3 1417.02   565.3 1417.78
   582.7 1417.91   605.9 1416.63   618.1 1415.18   621.7 1414.46   624.3 1414.38
  630.141415.178   639.1 1416.76   643.4 1418.16   647.7 1418.45   717.2 1418.64
   738.8 1418.94   758.7 1419.79   773.6 1420.95   780.1 1422.15   794.1 1425.48
#Mann= 3 ,-1,0
       0     .05       0   618.1    .045       0  630.14     .05       0
Bank Sta=618.1,630.14
XS Rating Curve= 0 ,0
Exp/Cntr(USF)=0,0
Exp/Cntr=0.3,0.1

Type RM Length L Ch R = 1 ,1385    ,181.5,181.9,180.8
XS GIS Cut Line= 3
2176039.02600161725935.7448015052176256.05389174725392.397540828
2176343.42320206725205.816339232
#Sta/Elev= 30
       0 1422.62    45.8 1421.45    93.2 1421.09     132 1421.65   144.9 1421.09
     166 1421.25   184.5 1420.63   192.3 1419.29   200.9 1418.59   218.1 1419.84
   230.6 1420.15   248.3 1417.87   292.2 1418.85   308.6 1419.88   319.9 1419.53
   329.1 1418.35   334.4 1418.15   467.9  1417.1   581.5 1417.83   593.1  1417.7
   601.9 1416.45   606.3 1416.38     624 1417.91   628.4 1417.48   633.81415.669
   638.7 1414.42   651.4 1415.64   665.8 1418.03   756.1  1418.9   791.1 1420.07
#Mann= 3 ,-1,0
       0     .05       0   633.8    .045       0   651.4     .05       0
#XS Ineff= 2 , 0
          315.49 1421.41
Permanent Ineff=
       F       F
Bank Sta=633.8,651.4
XS Rating Curve= 0 ,0
Exp/Cntr=0.3,0.1

Type RM Length L Ch R = 1 ,1203    ,219.7,222.7,221.4
XS GIS Cut Line= 2
2176210.11289932725945.2006039452176541.73042415725189.759705925
#Sta/Elev= 30
       0 1422.17    48.1 1421.81    65.5 1421.15   101.8 1420.87   122.3 1420.36
   134.5 1420.59   170.4 1420.27   184.3 1420.46   224.1 1419.76   286.9 1419.55
   349.5 1418.78   380.1 1418.84     498 1417.67   546.1 1417.57   559.2 1417.06
   563.6 1416.44   567.7 1414.99   572.2 1413.89   575.3 1413.86   578.4 1414.13
   582.3    1415   594.1 1417.62   598.5 1417.98     664 1418.47   677.1 1418.08
   720.2 1418.73   773.2 1420.44   782.5 1421.08   795.1 1422.59     825 1427.74
#Mann= 3 ,-1,0
       0     .05       0   567.7    .045       0   582.3     .05       0
Bank Sta=567.7,582.3
XS Rating Curve= 0 ,0
Exp/Cntr(USF)=0,0
Exp/Cntr=0.3,0.1

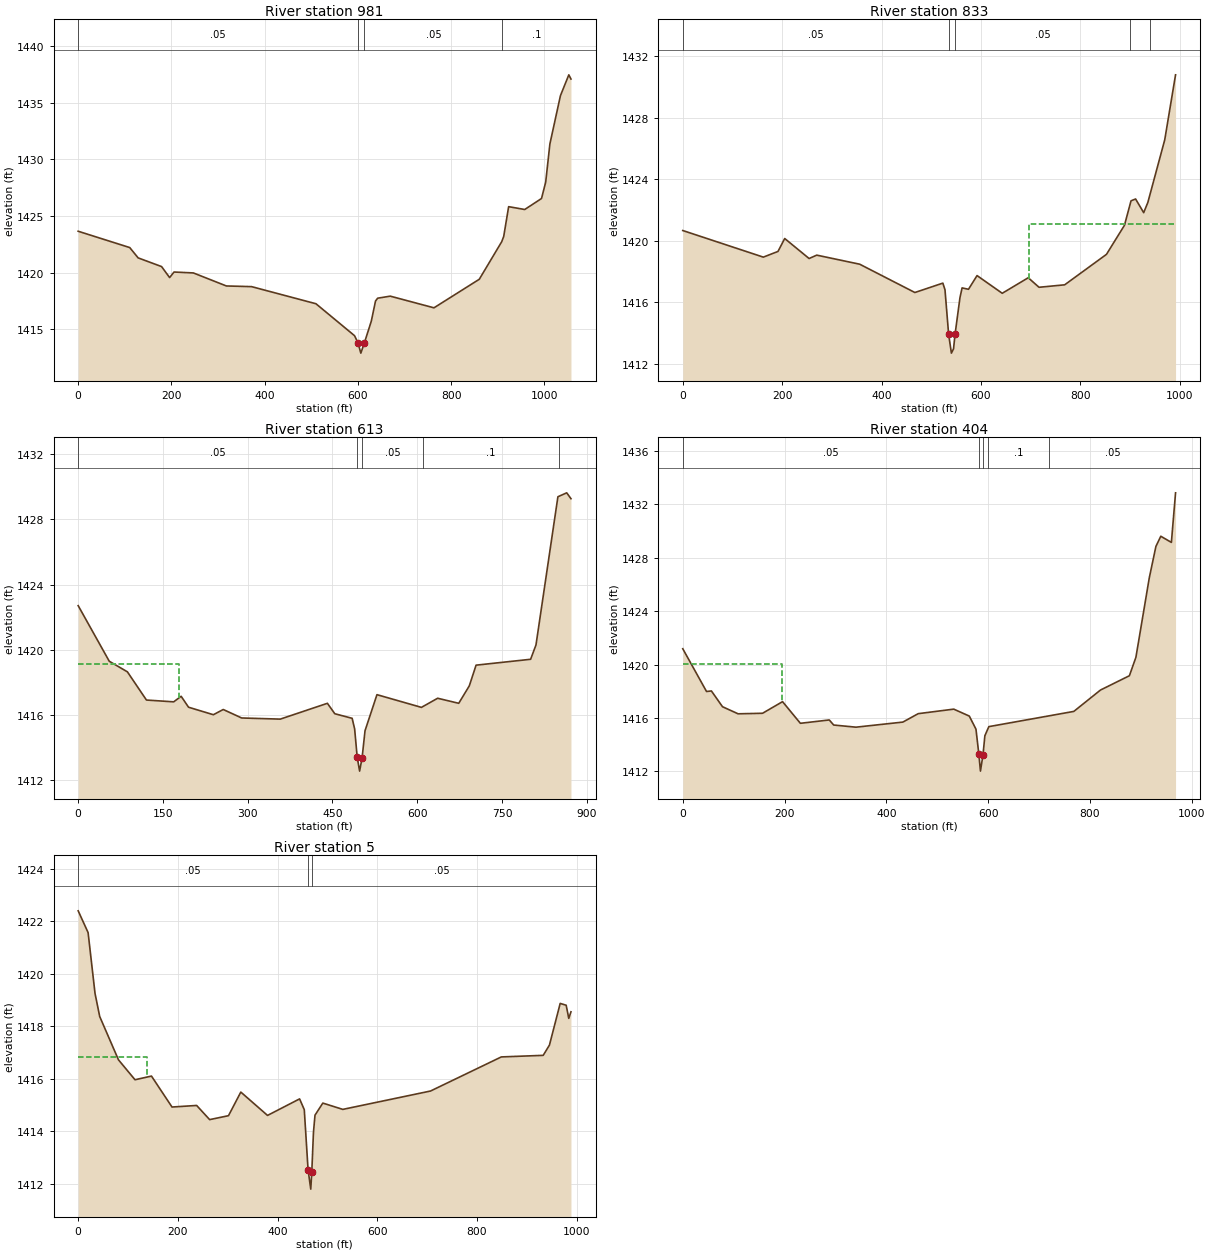
Type RM Length L Ch R = 1 ,981     ,148.4,148.1,145.8
XS GIS Cut Line= 2
2176353.10378923726059.3405842942176840.34571688725121.064765426
#Sta/Elev= 30
       0 1423.66   110.6 1422.22   128.6 1421.31   178.9 1420.54   196.2 1419.57
   205.6 1420.06   247.1 1419.98   317.9 1418.83     372 1418.77   510.1 1417.26
   592.9 1414.44   600.2 1413.81   606.4  1412.9   614.2 1413.83   628.9 1415.73
   637.9  1417.5   642.5 1417.75   669.5 1417.93   763.3  1416.9   860.5 1419.42
   908.7 1422.74   912.9  1423.2   923.5 1425.83     958 1425.58     994 1426.55
    1003    1428    1012 1431.37  1034.6 1435.63  1052.6 1437.47  1057.2  1437.1
#Mann= 4 ,-1,0
       0     .05       0   600.2    .045       0   614.2     .05       0
     910      .1       0
Bank Sta=600.2,614.2
XS Rating Curve= 0 ,0
Exp/Cntr(USF)=0,0
Exp/Cntr=0.3,0.1

Type RM Length L Ch R = 1 ,833     ,218.7,219.4,219.8
XS GIS Cut Line= 2
2176565.30892197726084.0310390672176928.85791117725161.567949639
#Sta/Elev= 30
       0 1420.66   162.1 1418.93   191.6  1419.3   205.1 1420.14   254.2 1418.84
   269.6 1419.06     356 1418.47     467 1416.63   523.3 1417.24   527.6 1416.81
   534.9 1413.92   540.5 1412.69   544.8 1412.97   547.91413.928   557.7 1416.29
     562 1416.93   574.9 1416.84   592.1 1417.73   642.8 1416.58   695.1 1417.59
   716.8 1416.97   768.4 1417.13   852.5 1419.11   888.7    1421   901.9 1422.59
   911.1 1422.71   927.4 1421.82   935.8 1422.49   969.7 1426.55   991.5 1430.78
#Mann= 5 ,-1,0
       0     .05       0   534.9    .045       0   547.9     .05       0
     900      .1       0     940     .05       0
#XS Ineff= 2 , 0
                           696.9         1421.08
Permanent Ineff=
       F       F
Bank Sta=534.9,547.9
XS Rating Curve= 0 ,0
Exp/Cntr(USF)=0,0
Exp/Cntr=0.3,0.1

Type RM Length L Ch R = 1 ,613     ,208.5,208.9,208.3
XS GIS Cut Line= 2
2176755.16045252726131.3068370192177112.95689064725336.096239472
#Sta/Elev= 30
       0 1422.71      55  1419.3    87.1 1418.65   120.8 1416.92     169 1416.81
   182.2 1417.15   195.3 1416.48   239.2 1416.02   256.7 1416.34   289.3 1415.82
   357.6 1415.75     441 1416.72   454.1 1416.08   484.8  1415.8   489.2 1415.15
   493.71413.427     498 1412.56   502.4 1413.38   507.6 1415.04   528.7 1417.25
   607.4 1416.47   636.1 1417.03   673.4 1416.72   692.1 1417.79   704.1 1419.06
   800.6 1419.42   810.1  1420.3   848.9 1429.39   864.5 1429.63     872 1429.27
#Mann= 5 ,-1,0
       0     .05       0   493.7    .045       0   502.4     .05       0
     610      .1       0     850     .05       0
#XS Ineff= 2 , 0
          179.15 1419.13
Permanent Ineff=
       F       F
Bank Sta=493.7,502.4
XS Rating Curve= 0 ,0
Exp/Cntr(USF)=0,0
Exp/Cntr=0.3,0.1

Type RM Length L Ch R = 1 ,404     ,399.1,399.1,399.1
XS GIS Cut Line= 3
2176914.19246263726296.7153445562177274.53822035725476.720209718
2177302.46274984725409.522108432
#Sta/Elev= 30
       0 1421.18    46.7 1417.98    56.3 1418.02    78.1 1416.84   108.7 1416.31
   156.8 1416.35   196.1 1417.22   231.1  1415.6   287.9 1415.85   296.6 1415.47
   340.3 1415.31   432.5 1415.69   462.6 1416.32   532.5 1416.66   563.1 1416.14
   576.2 1415.16   581.9 1413.27     585 1412.02     590 1413.24   593.7 1414.67
   601.5 1415.35   768.5 1416.49   820.9 1418.09   877.7 1419.16   890.5 1420.54
   916.8 1426.49   929.8 1428.84   939.4  1429.6   960.2 1429.14   968.4 1432.85
#Mann= 5 ,-1,0
       0     .05       0   581.9    .045       0     590     .05       0
     600      .1       0     720     .05       0
#XS Ineff= 2 , 0
          194.93 1420.07
Permanent Ineff=
       F       F
Bank Sta=581.9,590
XS Rating Curve= 0 ,0
Exp/Cntr(USF)=0,0
Exp/Cntr=0.3,0.1

Type RM Length L Ch R = 1 ,5       ,,,
XS GIS Cut Line= 4
2177241.43246285726353.8269702572177484.99219824 725963.97270029
2177691.57136705725574.7858682642177724.62463001725493.100964051
#Sta/Elev= 30
       0  1422.4    19.9 1421.57    33.8 1419.25    43.2 1418.37    80.8 1416.72
     114 1415.96     147  1416.1   188.2 1414.92   237.6 1414.98   263.7 1414.44
   301.5 1414.59   326.2 1415.49   379.8  1414.6   444.1 1415.23   453.5 1414.82
   461.1 1412.53   466.5 1411.79   468.61412.461   471.9 1413.95     475 1414.61
   490.7 1415.07   530.8 1414.83   706.7 1415.53   848.7 1416.83   932.7 1416.89
   945.2 1417.28   966.8 1418.87   978.8  1418.8     984  1418.3   988.4 1418.55
#Mann= 3 ,-1,0
       0     .05       0   461.1    .045       0   468.6     .05       0
#XS Ineff= 2 , 0
          137.78 1416.82
Permanent Ineff=
       F       F
Bank Sta=461.1,468.6
XS Rating Curve= 0 ,0
Exp/Cntr(USF)=0,0
Exp/Cntr=0.3,0.1
LCMann Table=0

Chan Stop Cuts=-1
Use User Specified Reach Order=0
Composite Channel Slope=5